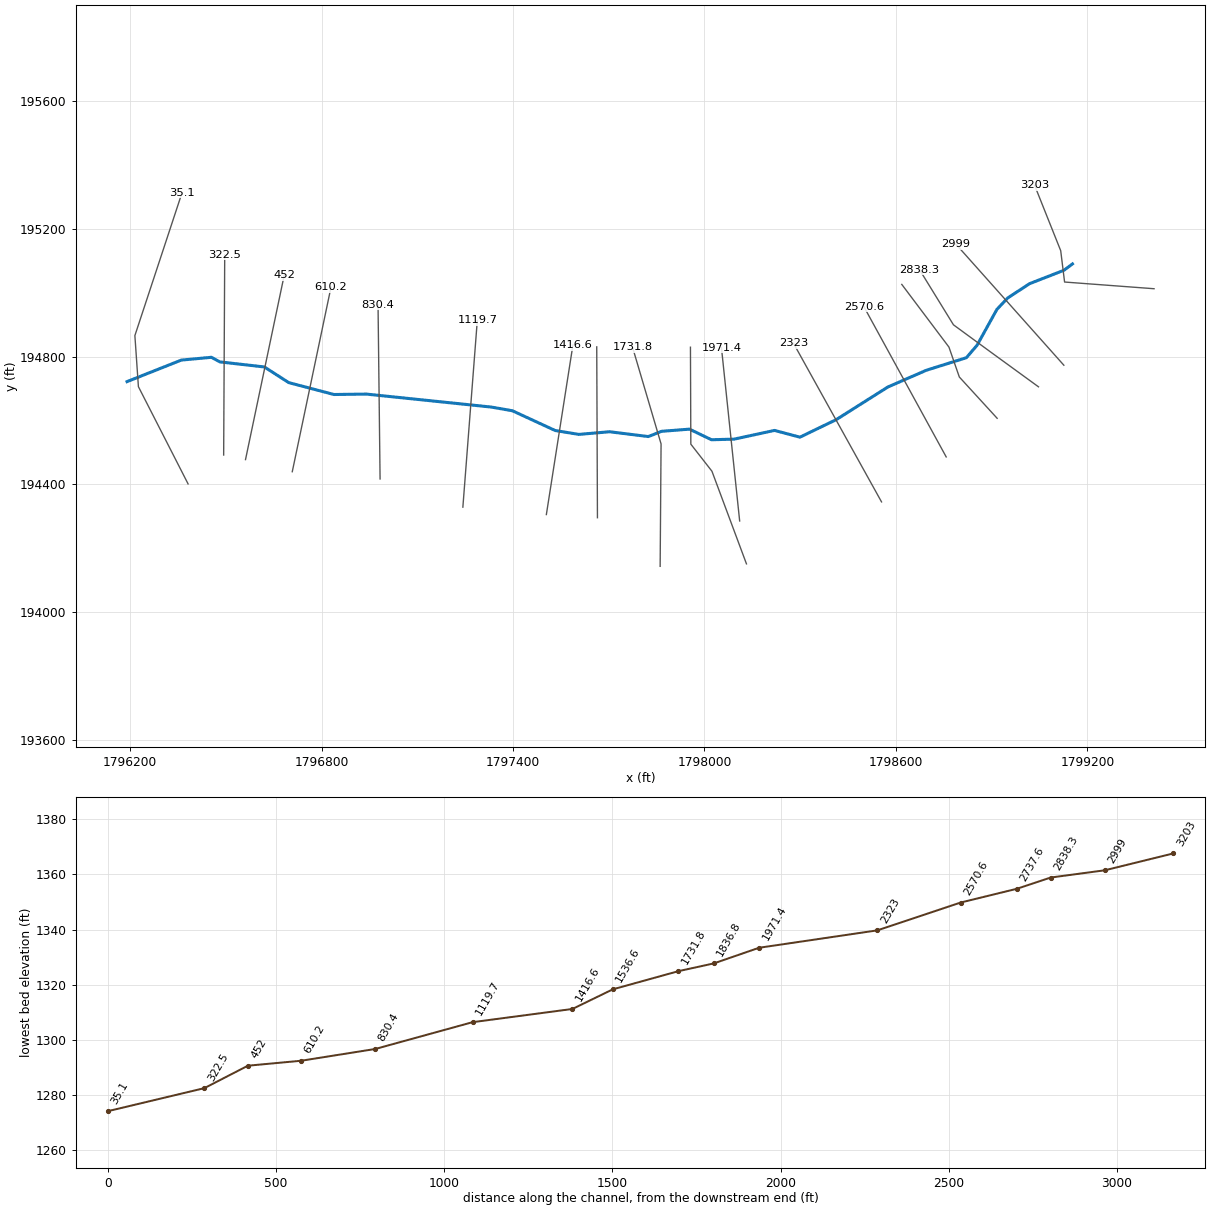
--- LickBr.prj (project) ---

Proj Title=LickBr
Current Plan=p01
Default Exp/Contr=0,0
English Units
Geom File=g01
Flow File=f01
Plan File=p01
BEGIN DESCRIPTION:
END DESCRIPTION:
DSS Export Rating Curves= 0
DSS Export Rating Curve Sorted= 0
DSS Export Volume Flow Curves= 0
DXF OffsetX= 0
DXF OffsetY= 0
DXF ScaleX= 0
DXF ScaleY= 0

--- LickBr.p01 (plan) ---

Plan Title=Floodplain
Program Version=4.00
Geom File=g01
Flow File=f01
K Sum by GR=0
Std Step Tol=0.01
Critical Tol=0.01
Num of Std Step Trials=20
Max Error Tol=0.3
Flow Tol Ratio=0.001
Split Flow NTrial=30
Split Flow Tol=0.02
Split Flow Ratio=0.02
Log Output Level=0
Friction Slope Method=1
Unsteady Friction Slope Method=2
Unsteady Bridges Friction Slope Method=1
Global Log Level=0
CheckData=False
Run HTab=0
Run UNet=0
Run PostProcess=0
UNET Theta=0
UNET Theta Warmup=0
UNET ZTol=0
UNET ZSATol=0
UNET MxIter=0
UNET MaxInSteps=0
UNET DtIC=0
UNET DtMin=0
UNET MaxCRTS=0
UNET WFStab=0
UNET SFStab=0
UNET WFX=0
UNET SFX=0
UNET DSS MLevel=0
UNET DZMax Abort=0
UNET Convert EG Bridges=0
UNET Use Existing IB Tables=0
UNET Froude Limit=0
UNET Froude Power=0
Write IC File=0
Echo Input=False
Echo Output=False
Write Detailed=0

--- LickBr.f01 (steady flow) ---

Flow Title=NFF Regression Equation
Program Version=4.00
Number of Profiles=1
Profile Names=P100yr
River Rch & RM=LickBr,Main      ,3203
501.5965
River Rch & RM=LickBr,Main      ,2999
502.7786
River Rch & RM=LickBr,Main      ,2737.6
663.5594
River Rch & RM=LickBr,Main      ,1836.8
679.9256
River Rch & RM=LickBr,Main      ,1536.6
744.7817
River Rch & RM=LickBr,Main      ,322.5
764.8714
Boundary for River Rch & Prof#=LickBr,Main      ,1
Up Type=0
Dn Type=3
Dn Slope=0.034571

--- LickBr.g01 (geometry) ---

Geom Title=USGS 10m DEM
Program Version=4.00

River Reach=LickBr          ,Main
Reach XY= 30
      1799153.02        195090.9     1799126.125      195070.998
     1799018.698      195029.166      1798950.18      194984.393
      1798916.26      194948.438     1798853.848      194835.825
     1798820.607      194797.156     1798695.104      194757.809
     1798575.029      194705.573     1798412.893      194603.136
     1798299.183      194548.169     1798219.364      194569.296
      1798093.37       194542.08     1798022.138      194540.045
     1797952.942      194573.286      1797865.43      194566.502
     1797824.092      194550.059     1797702.615      194565.146
     1797606.019      194556.837     1797532.201      194569.047
     1797398.017       194630.95     1797332.213      194642.482
     1796940.102      194683.186     1796839.021      194681.829
     1796697.237      194719.141     1796620.893      194768.191
     1796481.526      194783.996     1796454.938        194798.4
     1796360.754      194789.694     1796190.572      194722.236

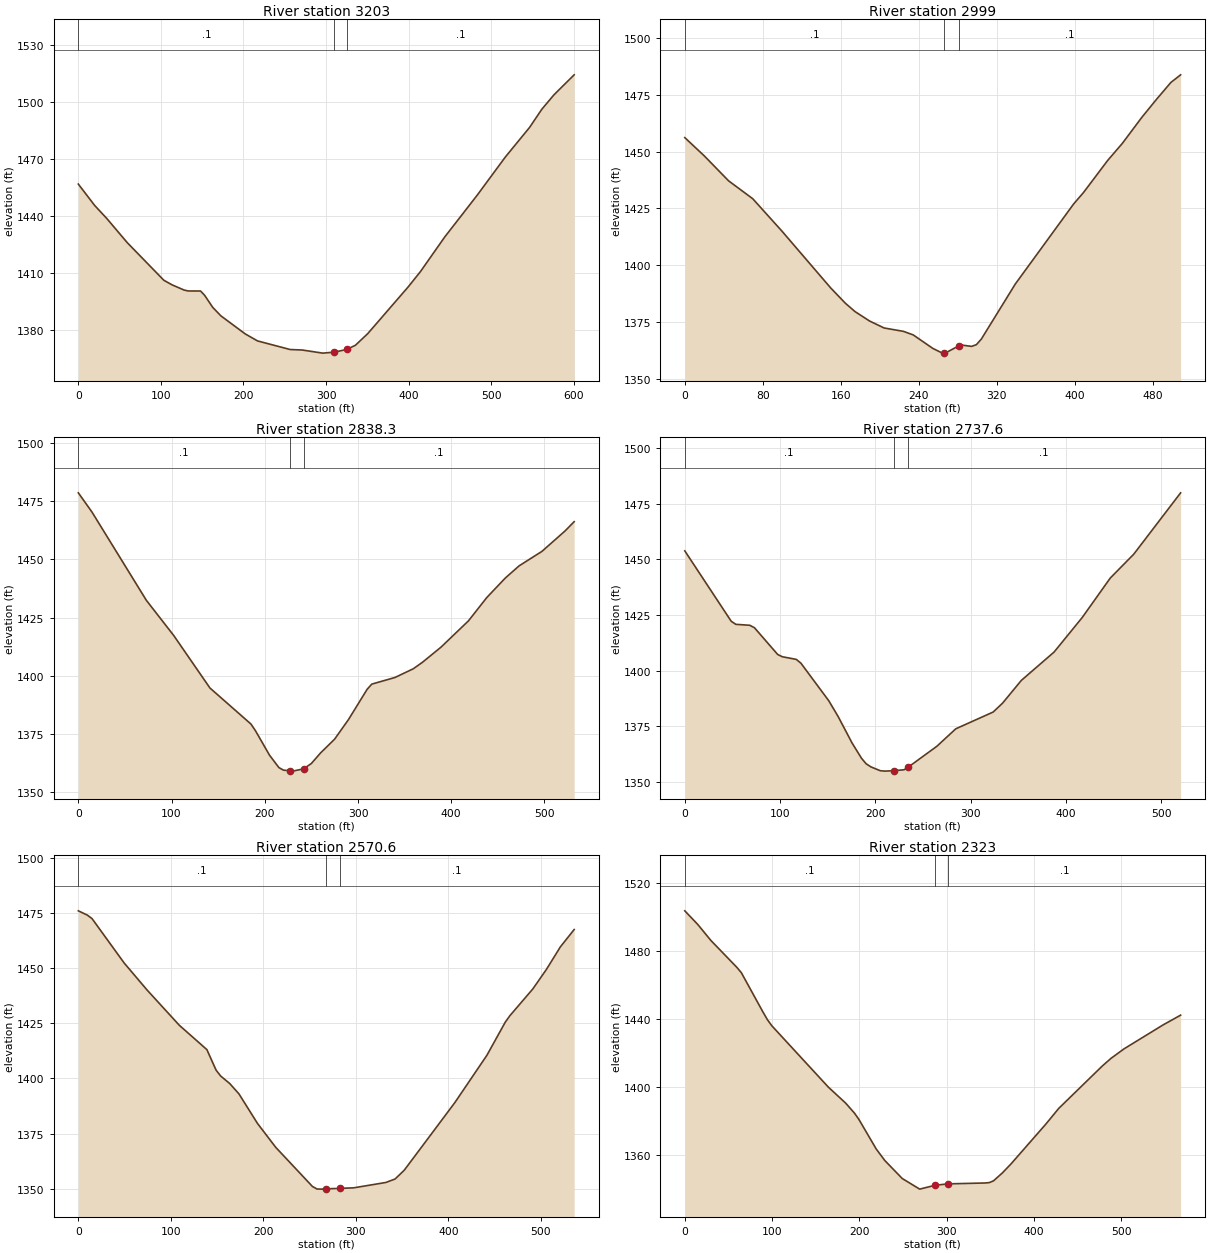
Type RM Length L Ch R = 1 ,3203    ,190.3,204,218.4
XS GIS Cut Line= 4
     1799408.717      195013.282     1799128.334      195034.256
     1799116.191        195132.5     1799034.483      195337.132
#Sta/Elev= 30
       0 1456.58    19.7 1445.38    34.5 1438.46    59.2 1425.79   103.6 1405.96
   113.4 1403.58   128.2 1400.81   133.2 1400.33     148 1400.32   152.9 1398.09
   162.8  1391.7   172.6 1387.26   202.2 1377.72     217 1374.06   256.5 1369.53
   271.3 1369.26     296 1367.63     310 1368.14     325 1369.55   335.6 1371.77
   350.5 1377.88   399.7 1402.58   414.4 1410.57   443.8 1428.77     483 1450.69
   517.3  1470.9   546.6 1486.44   561.3 1495.93     576 1503.53   600.5 1514.07
#Mann= 3 , 0 , 0
       0      .1       0     310    .045       0     325      .1       0
Bank Sta=310,325
XS Rating Curve= 0 ,0
Exp/Cntr=0.3,0.1

Type RM Length L Ch R = 1 ,2999    ,156.1,160.8,165.4
XS GIS Cut Line= 2
     1799126.034      194773.627     1798787.514      195153.359
#Sta/Elev= 30
       0 1456.11      20 1448.09    44.9 1437.16    69.8 1429.25    99.8    1415
   149.6 1390.16   164.6 1383.46   174.6 1379.75   189.5 1375.62   204.5 1372.54
   224.4 1371.05   234.4 1369.49   254.4 1363.59   264.3  1361.5   266.1 1361.67
   269.3    1362   281.1 1364.69   284.3 1365.03   294.3 1364.46   299.2 1365.23
   304.2 1367.64   339.1 1391.85     399 1427.02     409 1431.97   433.9 1446.11
   448.9 1453.58   468.8 1464.96   483.8 1472.84   498.7 1480.33   508.7 1483.68
#Mann= 3 , 0 , 0
       0      .1       0   266.1    .045       0   281.1      .1       0
Bank Sta=266.1,281.1
XS Rating Curve= 0 ,0
Exp/Cntr=0.3,0.1

Type RM Length L Ch R = 1 ,2838.3  ,114.4,100.7,86.9
XS GIS Cut Line= 4
     1799046.556      194705.923     1798900.845      194811.895
     1798780.154      194900.204     1798674.183      195072.408
#Sta/Elev= 30
       0 1478.71    14.6 1470.46      73 1432.41   102.3 1417.29   141.2 1394.66
   185.2 1379.14   190.1 1376.22   205.1 1365.74   215.1 1360.42     220  1359.3
   226.6 1359.02     230 1358.87   241.6 1359.85     250 1362.16   259.9 1366.72
   274.9 1372.62   289.8 1381.06   309.8 1394.09   314.8 1396.34   339.6 1399.18
   359.3 1402.94   369.2 1405.75   388.9  1412.2   418.5 1423.57   438.2 1433.63
   457.9 1441.96   472.7 1447.22   497.4 1453.52     522 1462.24   531.9 1466.28
#Mann= 3 , 0 , 0
       0      .1       0   226.6    .045       0   241.6      .1       0
Bank Sta=226.6,241.6
XS Rating Curve= 0 ,0
Exp/Cntr=0.3,0.1

Type RM Length L Ch R = 1 ,2737.6  ,163.2,167,170.8
XS GIS Cut Line= 4
     1798917.035       194607.31     1798798.515      194736.719
     1798766.054      194830.316     1798618.253      195026.782
#Sta/Elev= 30
       0 1453.84    48.7  1422.2    53.6  1420.8    68.2 1420.38    73.1 1419.28
    97.5 1407.24   102.4 1406.22     117 1405.04   121.9 1403.32   151.1 1386.44
   160.9 1379.38   175.5 1367.49   185.4  1360.6   190.3  1358.1   195.3  1356.7
   205.2 1354.96   210.2 1354.78   219.1 1354.97     230 1355.38   234.1 1356.44
   264.6 1365.97   284.4 1373.81   323.7 1381.37   333.6 1385.39   353.2 1395.58
   387.6 1408.34   417.1 1423.86   446.6 1441.64   471.2 1452.35   520.4 1479.95
#Mann= 3 , 0 , 0
       0      .1       0   219.1    .045       0   234.1      .1       0
Bank Sta=219.1,234.1
XS Rating Curve= 0 ,0
Exp/Cntr=0.3,0.1

Type RM Length L Ch R = 1 ,2570.6  ,247.5,247.6,247.7
XS GIS Cut Line= 2
     1798757.397      194486.226     1798499.871      194956.374
#Sta/Elev= 30
       0 1476.04     9.9 1474.06    14.9 1472.47    49.6 1452.35    74.4 1440.09
   109.2 1424.12     139 1413.08   148.9 1403.81   153.9 1401.11   163.8 1397.65
   173.7 1392.98   193.6 1379.66   213.4 1368.77   253.1    1351   258.1 1349.84
   263.1 1349.79   267.7 1349.93   282.7 1350.13   297.8 1350.38   332.6 1352.82
   342.5 1354.39   352.4 1358.37     407 1388.99   441.8 1410.53   461.6 1425.53
   466.6 1428.46   491.4  1440.6   506.3 1449.58   521.2  1459.7   536.1 1467.55
#Mann= 3 , 0 , 0
       0      .1       0   267.7    .045       0   282.7      .1       0
Bank Sta=267.7,282.7
XS Rating Curve= 0 ,0
Exp/Cntr=0.3,0.1

Type RM Length L Ch R = 1 ,2323    ,360.4,351.5,342.1
XS GIS Cut Line= 2
     1798554.772      194345.331      1798279.25      194841.803
#Sta/Elev= 30
       0 1503.39    14.9 1495.35    29.9 1485.95    59.8 1470.04    64.8 1466.96
    89.6 1443.79    94.6 1439.37    99.6 1435.81   164.4 1399.69   184.3 1390.24
   194.2 1384.46   199.2 1380.85   219.2 1363.31   229.1 1356.49     249 1345.94
     269 1339.69   286.8 1341.98   301.8 1342.79   343.7  1343.3   348.6 1343.51
   353.6  1344.6   363.6 1349.19   373.6 1354.54   413.4  1377.9   428.3 1387.22
   478.2 1412.16   488.1 1416.61     503 1422.21   547.9 1436.34   567.8 1442.03
#Mann= 3 , 0 , 0
       0      .1       0   286.8    .045       0   301.8      .1       0
Bank Sta=286.8,301.8
XS Rating Curve= 0 ,0
Exp/Cntr=0.3,0.1

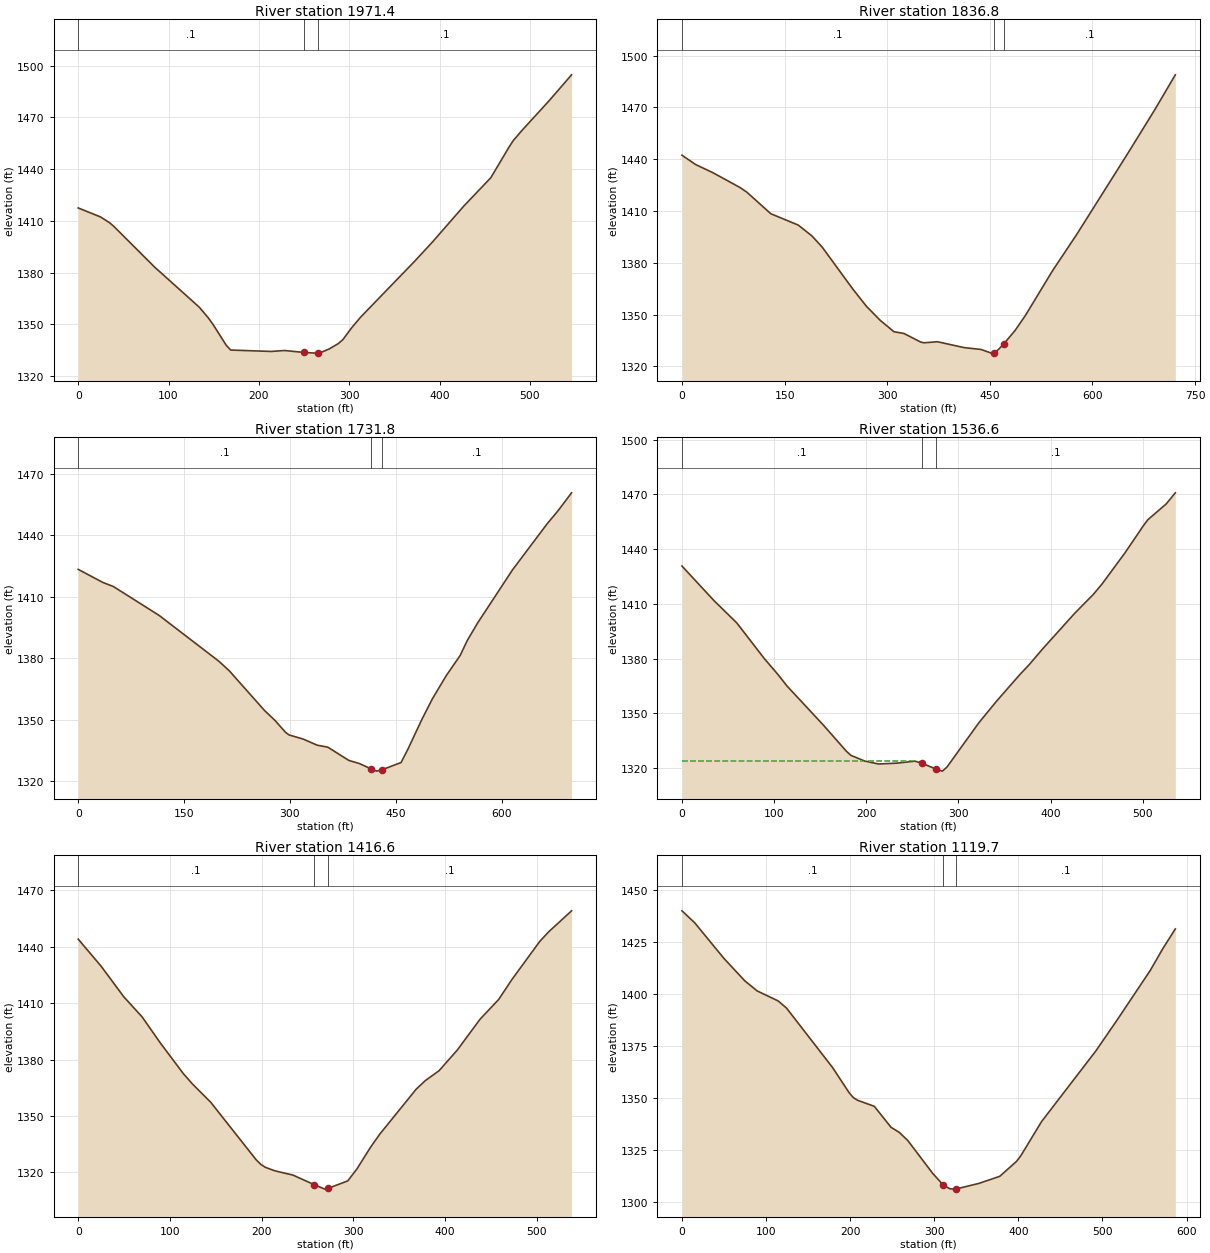
Type RM Length L Ch R = 1 ,1971.4  ,137.1,134.6,132.1
XS GIS Cut Line= 2
     1798110.233      194285.588     1798053.132      194828.813
#Sta/Elev= 30
       0  1417.5    24.8 1412.26    34.8 1408.92    39.7  1406.7    84.4 1383.32
   134.1 1359.96     144 1353.82     149 1350.22   163.9 1337.92   168.8 1335.16
   213.5 1334.34   228.4 1334.89   250.2 1333.75   263.2 1333.37   265.2 1333.46
   268.1 1333.58   278.1 1335.86     288 1338.92     293 1341.18   302.9 1348.17
   312.8  1354.3   372.4 1386.57   392.3 1397.83     427 1418.65   456.8 1435.01
   476.7 1452.54   481.7 1456.57   491.6  1462.6   521.4 1479.66   546.2 1494.64
#Mann= 3 , 0 , 0
       0      .1       0   250.2    .045       0   265.2      .1       0
Bank Sta=250.2,265.2
XS Rating Curve= 0 ,0
Exp/Cntr=0.3,0.1

Type RM Length L Ch R = 1 ,1836.8  ,98.7,105,111.2
XS GIS Cut Line= 4
     1798131.538      194151.158     1798023.359      194441.477
     1797957.226      194526.262     1797956.022      194830.039
#Sta/Elev= 30
       0 1442.31      20  1436.9      45 1432.23      85 1423.56    94.9 1420.89
   129.9 1408.41   169.9 1401.86   189.9 1395.59   204.9 1389.12   249.8 1364.76
   269.8 1354.74   289.8 1346.67   309.8  1340.1   324.5 1339.06   348.9  1334.1
   353.8 1333.67   373.4 1334.29   412.5 1330.88   437.3  1329.8   452.2 1327.69
   455.7 1327.93   462.2 1329.65   470.7 1333.15   487.1 1340.92     502 1349.52
   541.8 1375.51   576.7 1396.24   651.4  1443.2   691.2 1468.72   721.1 1488.86
#Mann= 3 , 0 , 0
       0      .1       0   455.7    .045       0   470.7      .1       0
Bank Sta=455.7,470.7
XS Rating Curve= 0 ,0
Exp/Cntr=0.3,0.1

Type RM Length L Ch R = 1 ,1731.8  ,201.7,195.3,188.8
XS GIS Cut Line= 3
     1797861.089      194143.431     1797863.967      194526.998
     1797774.681      194829.622
#Sta/Elev= 30
       0 1423.35    34.9 1416.97    49.8 1414.98   114.6 1400.89   199.3 1378.52
   214.2  1373.8     264 1354.48     279 1349.56   293.9 1343.78   298.9 1342.53
   318.8 1340.52   338.7 1337.53   353.7 1336.57   383.6 1330.09   398.4 1328.59
   414.8    1326     423 1324.88   429.8 1325.46   457.5 1329.08   467.4 1335.73
   487.1 1350.19   501.9 1360.18   521.6 1371.52   541.3 1381.36   551.2 1388.57
     566 1397.19   615.3 1423.05   664.6 1445.64   679.4 1451.72   699.1  1460.7
#Mann= 3 , 0 , 0
       0      .1       0   414.8    .045       0   429.8      .1       0
Bank Sta=414.8,429.8
XS Rating Curve= 0 ,0
Exp/Cntr=0.3,0.1

Type RM Length L Ch R = 1 ,1536.6  ,123.5,119.9,116.4
XS GIS Cut Line= 2
       1797664.6      194295.766     1797662.392      194831.143
#Sta/Elev= 30
       0 1430.71    34.7 1411.78    59.5 1399.52    89.2 1380.08   104.1 1371.28
     114 1364.94   153.7 1343.38   178.5 1329.13   183.4  1326.9   198.3  1323.8
   213.2 1322.18     233 1322.64   252.8 1323.75   260.9 1322.49   275.9 1319.37
   282.6 1318.27   287.5 1320.44   322.2 1344.79     342 1356.98   366.8 1371.27
   376.8 1376.63   391.6 1385.39   426.3 1404.85   446.2 1415.03   456.1    1421
   480.8 1437.96   500.7 1452.78   505.6  1456.1   525.5 1464.75   535.4 1470.84
#Mann= 3 , 0 , 0
       0      .1       0   260.9    .045       0   275.9      .1       0
#XS Ineff= 2 , 0
          252.44 1323.75
Permanent Ineff=
       F       F
Bank Sta=260.9,275.9
XS Rating Curve= 0 ,0
Exp/Cntr=0.3,0.1

Type RM Length L Ch R = 1 ,1416.6  ,294.9,296.9,298.9
XS GIS Cut Line= 2
     1797504.539        194305.7     1797587.772      194837.063
#Sta/Elev= 30
       0 1444.09    24.9 1429.74    49.8 1413.36    69.7 1402.72    89.6 1388.82
   114.5 1372.63   124.5 1367.09   144.4 1357.38   194.2 1326.63   199.2 1324.24
   204.2 1322.72   214.1 1320.92   234.1 1318.61   257.3 1313.52   268.9 1311.15
   272.3 1311.55   293.8 1315.52   303.8 1321.87   318.7 1333.44   328.7 1340.36
   368.5 1364.34   378.5  1368.9   393.4 1374.14   413.3 1385.15   438.2  1401.6
   458.2 1411.92   473.1 1422.83     503  1442.8   512.9    1448   537.8 1459.14
#Mann= 3 , 0 , 0
       0      .1       0   257.3    .045       0   272.3      .1       0
Bank Sta=257.3,272.3
XS Rating Curve= 0 ,0
Exp/Cntr=0.3,0.1

Type RM Length L Ch R = 1 ,1119.7  ,287.3,289.3,291.3
XS GIS Cut Line= 2
     1797242.921      194328.882     1797288.152      194913.789
#Sta/Elev= 30
       0 1440.14    14.9 1434.51    49.7 1417.36    74.6 1406.53    89.5 1401.62
   114.4 1396.82   124.3  1393.4     179 1364.84   198.9 1352.62   203.8 1350.34
   208.8 1349.07   228.7 1346.16   248.6 1336.08   258.5 1333.59   268.5 1329.72
   298.3 1313.83   310.6 1308.38   318.2 1306.57   323.2 1306.35   325.6 1306.38
     353  1309.1   377.8 1312.49   397.7 1319.66   402.7 1322.27   427.6 1338.84
   492.2 1372.84     517 1387.41   556.8 1411.48   571.7 1421.95   586.6 1431.44
#Mann= 3 , 0 , 0
       0      .1       0   310.6    .045       0   325.6      .1       0
Bank Sta=310.6,325.6
XS Rating Curve= 0 ,0
Exp/Cntr=0.3,0.1

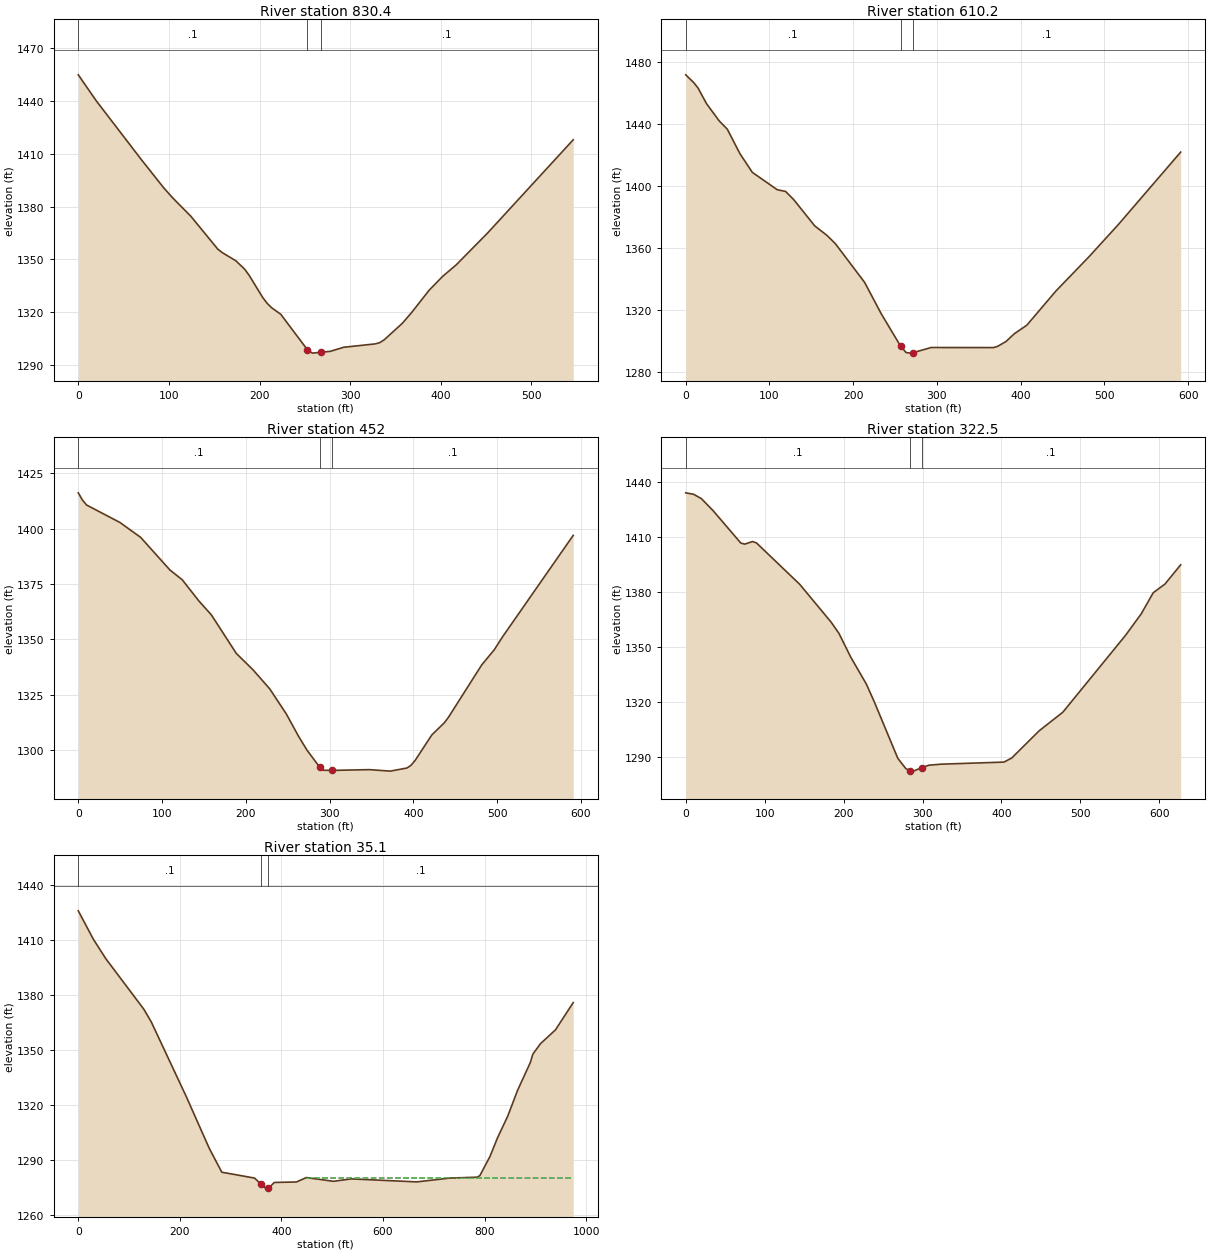
Type RM Length L Ch R = 1 ,830.4   ,225.1,220.2,215.2
XS GIS Cut Line= 2
     1796983.511      194417.192     1796977.123      194963.245
#Sta/Elev= 30
       0  1454.9    19.9 1440.07    69.5 1406.74    94.3 1390.61   104.2 1384.89
   124.1 1374.53   153.9 1355.79   158.9 1353.76   173.8 1349.17   183.7  1344.3
   188.6 1340.82   203.5 1328.25   208.5 1324.88   213.5 1322.37   223.4 1318.73
   252.8 1298.56   258.2 1296.62   267.8 1297.12     278 1297.63   292.9 1299.96
   327.6 1301.87   332.6 1302.57   337.6 1304.22   357.4 1313.51   367.4 1319.45
   387.2 1332.44   402.1  1340.3     417 1346.82   451.8 1365.02   546.1 1417.96
#Mann= 3 , 0 , 0
       0      .1       0   252.8    .045       0   267.8      .1       0
Bank Sta=252.8,267.8
XS Rating Curve= 0 ,0
Exp/Cntr=0.3,0.1

Type RM Length L Ch R = 1 ,610.2   ,158.1,158.2,158.3
XS GIS Cut Line= 2
     1796708.352      194439.876     1796829.778      195018.305
#Sta/Elev= 30
       0 1471.69     9.9 1466.49    14.9 1463.01    24.8 1453.13    39.7 1442.17
    49.7 1436.61    64.6 1420.98    79.5 1408.84   109.3 1397.64   119.2 1396.55
   129.1 1391.17     154 1374.36   168.9 1368.11   178.8 1362.81   213.6 1337.93
   233.4 1317.77   256.5 1296.91   263.2  1292.7   268.2 1292.35   271.5 1292.63
     293 1295.97   367.5 1295.93   372.5 1296.74   382.4 1299.83   392.4 1304.86
   407.3 1310.35     442 1332.36   481.8 1354.62   516.5 1375.16     591 1421.89
#Mann= 3 , 0 , 0
       0      .1       0   256.5    .045       0   271.5      .1       0
Bank Sta=256.5,271.5
XS Rating Curve= 0 ,0
Exp/Cntr=0.3,0.1

Type RM Length L Ch R = 1 ,452     ,124.9,129.5,134.1
XS GIS Cut Line= 2
     1796561.839       194477.87     1796683.265      195056.299
#Sta/Elev= 30
       0 1416.14       5 1412.86     9.9 1410.65    49.7 1402.77    74.5 1396.04
   109.3 1381.37   124.2 1376.88     144 1367.34   158.9 1361.07   188.7 1343.67
   208.6 1336.29   228.5 1327.73   248.3 1316.42   263.2 1306.16   273.2 1299.97
   288.4 1292.27     293 1290.94   303.4 1290.88   347.7 1291.22   372.5 1290.55
   392.4 1291.95   397.3 1293.17   402.3 1295.42   422.2  1306.9   437.1 1312.37
     442 1314.83   481.8 1338.51   496.7 1345.31   506.6 1351.14     591 1396.94
#Mann= 3 , 0 , 0
       0      .1       0   288.4    .045       0   303.4      .1       0
Bank Sta=288.4,303.4
XS Rating Curve= 0 ,0
Exp/Cntr=0.3,0.1

Type RM Length L Ch R = 1 ,322.5   ,285.2,287.4,289.4
XS GIS Cut Line= 2
     1796493.392      194492.255     1796496.704      195119.254
#Sta/Elev= 30
       0 1433.99      10  1433.2    19.9  1430.8    34.8 1424.22    69.7 1406.66
    74.6 1406.04    84.6 1407.46    89.6 1406.71   144.3  1384.2   184.1  1363.6
   194.1 1357.43     209 1344.52   228.9 1329.75   238.9 1320.11   268.7 1289.34
   278.7 1283.84   283.7 1282.59   288.6  1282.4   298.7 1284.32   308.5 1285.65
   323.5 1286.19   403.1 1287.32     413 1289.55   447.9 1304.43   477.7 1314.48
   557.3 1356.44   577.2 1368.18   592.2 1379.55   607.1  1384.3     627 1394.77
#Mann= 3 , 0 , 0
       0      .1       0   283.7    .045       0   298.7      .1       0
Bank Sta=283.7,298.7
XS Rating Curve= 0 ,0
Exp/Cntr=0.3,0.1

Type RM Length L Ch R = 1 ,35.1    ,30.8,35.1,39.4
XS GIS Cut Line= 4
     1796381.901      194401.737     1796226.255      194706.406
     1796215.217      194866.467     1796363.135      195314.639
#Sta/Elev= 30
       0 1425.69    29.8 1410.15    54.5 1399.49   128.9 1372.14   143.8 1365.09
   213.2 1324.12   257.8  1296.3   282.6 1283.24     347 1280.05   359.5 1276.79
   371.3 1274.02   374.5  1274.5   385.9 1277.66   429.6 1277.91   449.1 1280.33
   502.6 1278.27   537.3  1279.6   666.5 1277.96   731.1 1280.03   785.7 1280.53
   790.7 1281.39   810.6  1291.8   825.5 1302.01   845.4 1313.68   865.2 1328.01
   890.1 1343.04     895 1347.58   909.9 1353.24   939.7 1360.86   974.5 1375.68
#Mann= 3 , 0 , 0
       0      .1       0   359.5    .045       0   374.5      .1       0
#XS Ineff= 2 , 0
                          448.28         1280.28
Permanent Ineff=
       F       F
Bank Sta=359.5,374.5
XS Rating Curve= 0 ,0
Exp/Cntr=0.3,0.1

Chan Stop Cuts=-1
Use User Specified Reach Order=0